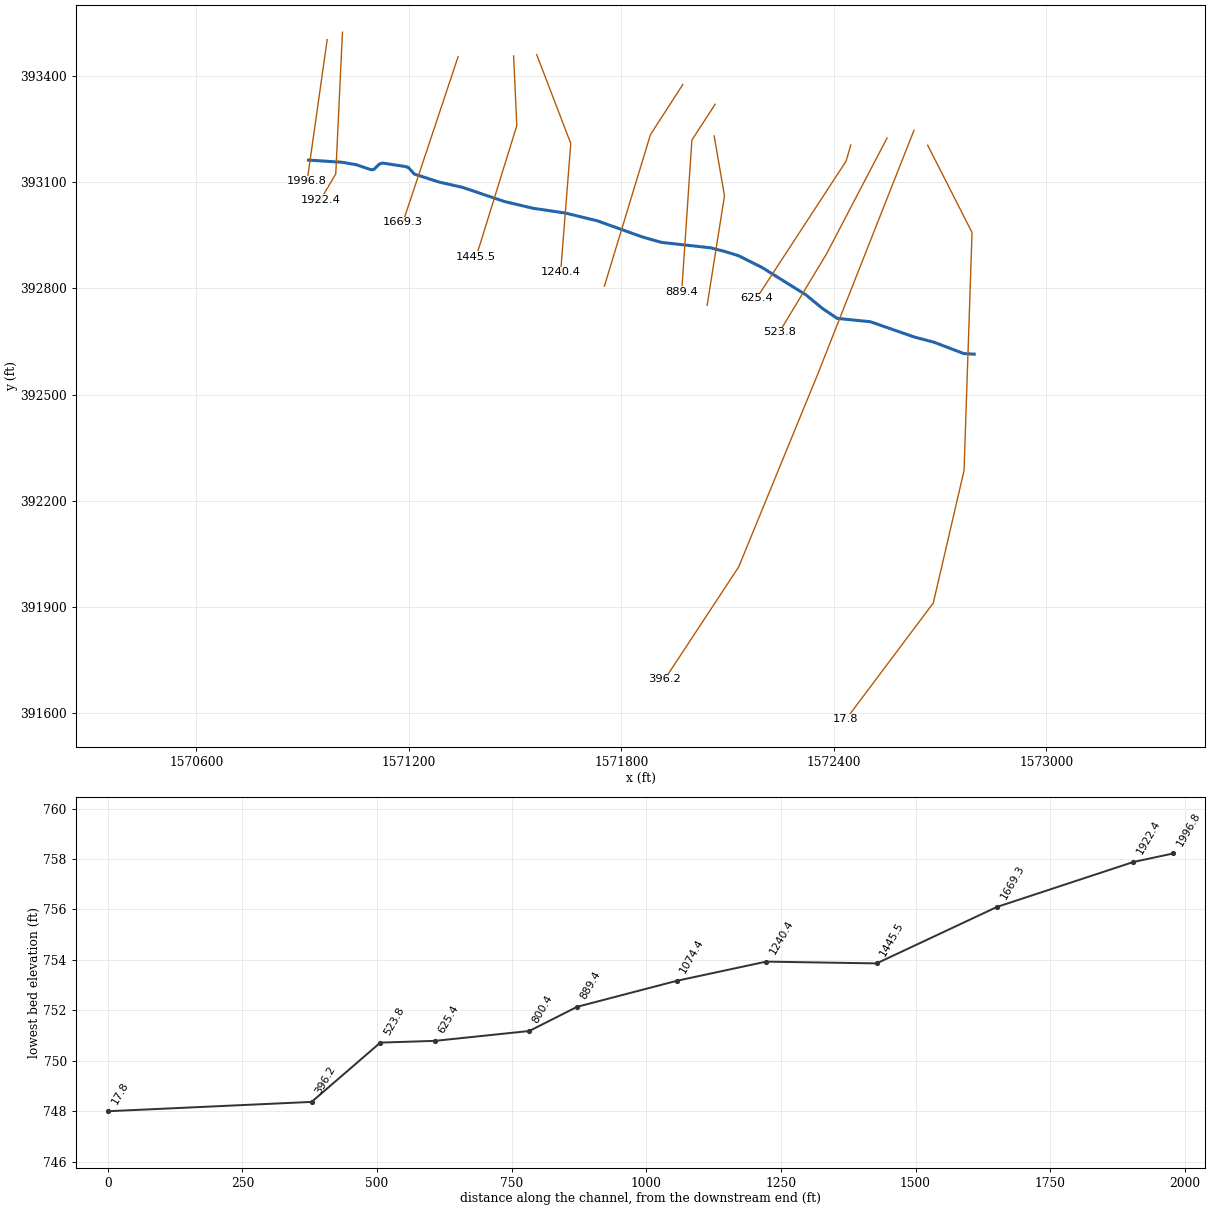
--- BUCKRN.prj (project) ---

Proj Title=BUCKRN
Current Plan=p01
Default Exp/Contr=0,0
English Units
Geom File=g01
Flow File=f01
Plan File=p01
BEGIN DESCRIPTION:
END DESCRIPTION:
DSS Export Rating Curves= 0
DSS Export Rating Curve Sorted= 0
DSS Export Volume Flow Curves= 0
DXF Filename=..\..\..\..\04_EngrWorking\AFG\Approximate\BUCKRN\BUCKRN.
DXF OffsetX= 0
DXF OffsetY= 0
DXF ScaleX= 0
DXF ScaleY= 0

--- BUCKRN.p01 (plan) ---

Plan Title=Floodplain
Program Version=4.00
Geom File=g01
Flow File=f01
K Sum by GR=0
Std Step Tol=0.01
Critical Tol=0.01
Num of Std Step Trials=20
Max Error Tol=0.3
Flow Tol Ratio=0.001
Split Flow NTrial=30
Split Flow Tol=0.02
Split Flow Ratio=0.02
Log Output Level=0
Friction Slope Method=1
Unsteady Friction Slope Method=2
Unsteady Bridges Friction Slope Method=1
Global Log Level=0
CheckData=False
Run HTab=0
Run UNet=0
Run PostProcess=0
UNET Theta=0
UNET Theta Warmup=0
UNET ZTol=0
UNET ZSATol=0
UNET MxIter=0
UNET MaxInSteps=0
UNET DtIC=0
UNET DtMin=0
UNET MaxCRTS=0
UNET WFStab=0
UNET SFStab=0
UNET WFX=0
UNET SFX=0
UNET DSS MLevel=0
UNET DZMax Abort=0
UNET Convert EG Bridges=0
UNET Use Existing IB Tables=0
UNET Froude Limit=0
UNET Froude Power=0
Write IC File=0
Echo Input=False
Echo Output=False
Write Detailed=0

--- BUCKRN.f01 (steady flow) ---

Flow Title=NFF Regression Equation
Program Version=4.10
Number of Profiles= 1
Profile Names=P100yr
River Rch & RM=BUCKRN,Main            ,1996.8
1000.958
River Rch & RM=BUCKRN,Main            ,625.4
1045.002
Boundary for River Rch & Prof#=BUCKRN,Main            , 1
Up Type= 0
Dn Type= 3
Dn Slope=0.001
DSS Import GetInterval= 0
DSS Import GetPeak= 0
DSS Import FillOption= 0

--- BUCKRN.g01 (geometry) ---

Geom Title=USGS 10m DEM
Program Version=4.10

River Reach=BUCKRN          ,Main
Reach XY= 30
     1570916.773      393161.949     1571010.709      393155.902
     1571051.837      393148.891     1571092.772      393134.953
     1571101.105      393135.213     1571117.021      393151.004
     1571126.157      393153.542     1571189.169      393143.851
     1571198.414      393141.246     1571215.602      393122.366
     1571285.245      393099.955     1571350.783      393085.198
     1571469.349       393045.17     1571550.599      393025.899
     1571643.109      393012.227     1571733.284      392990.134
      1571859.03      392945.007     1571914.142      392929.429
     1572052.163      392914.238     1572092.527      392903.821
     1572130.871      392891.994     1572195.667      392859.637
     1572320.602      392781.902     1572368.247      392742.754
     1572409.673      392714.978     1572503.561      392705.424
     1572628.127      392662.021     1572681.941      392648.054
     1572766.953      392615.641      1572796.56       392614.03

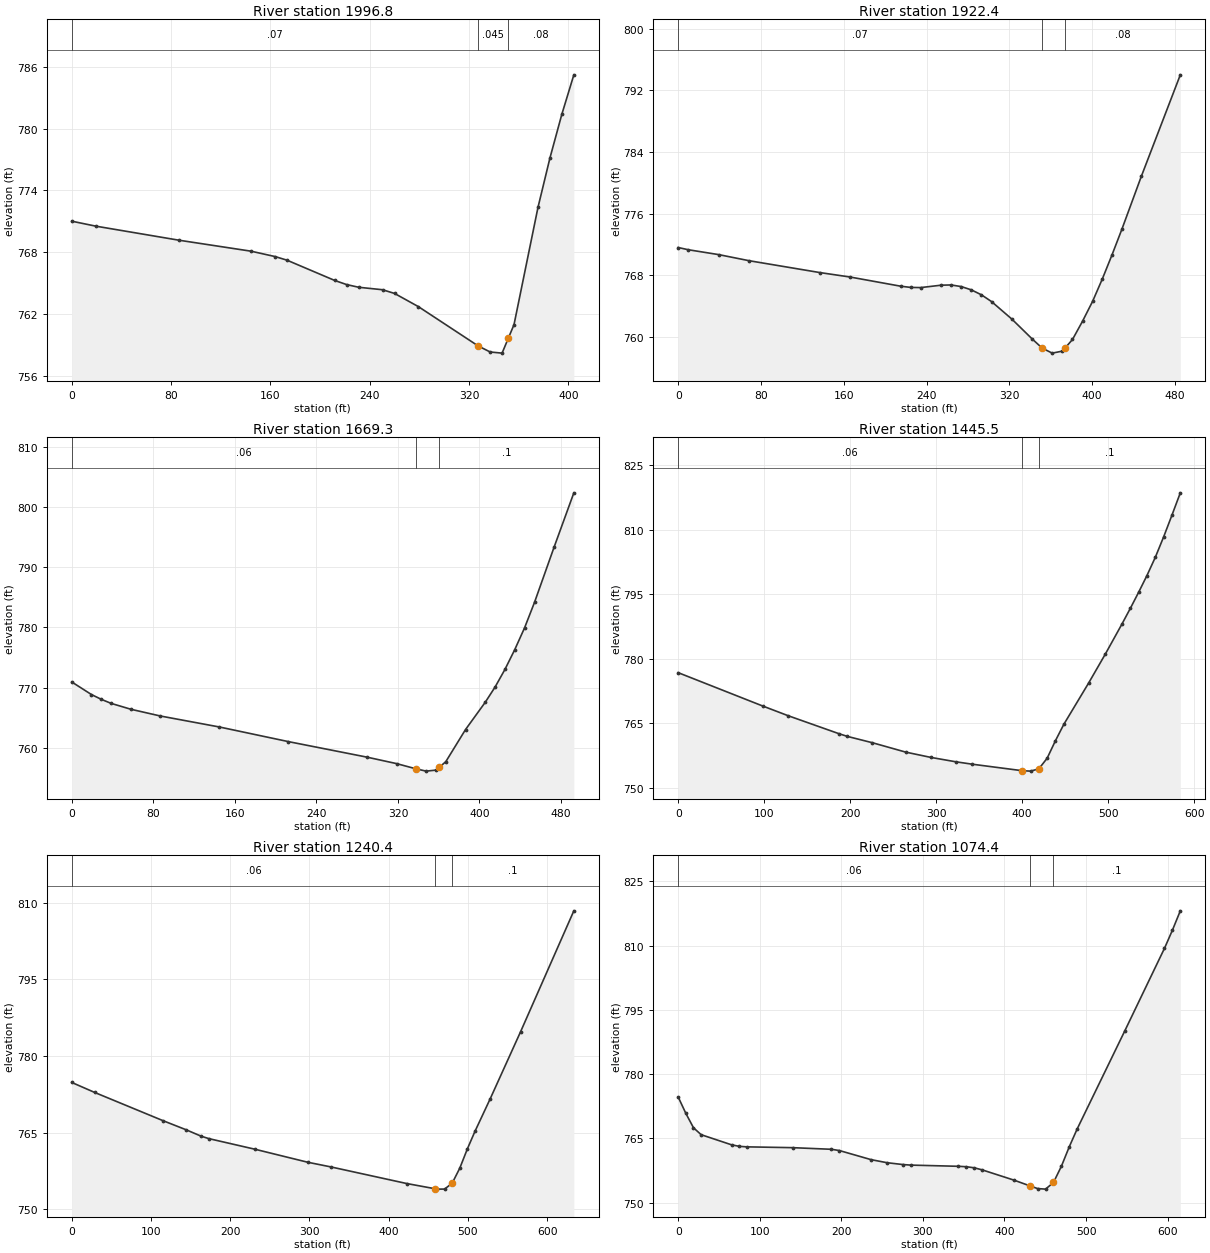
Type RM Length L Ch R = 1 ,1996.8  ,72.1,74.4,76.4
XS GIS Cut Line= 2
     1570969.415      393502.023     1570912.633      393101.665
#Sta/Elev= 21
       0  771.02    19.3  770.54    86.6  769.17   144.4  768.11   163.7  767.59
   173.3  767.24   211.8  765.27   221.4  764.87   231.1  764.61   250.3  764.37
     260  764.01   279.2  762.73   327.3  758.92     337  758.33   346.6  758.22
   351.7  759.69   356.2  760.98   375.5  772.35   385.1  777.13   394.7  781.38
   404.4  785.22
#Mann= 3 , 0 , 0
       0     .07       0   327.3    .045       0   351.7     .08       0
Bank Sta=327.3,351.7
XS Rating Curve= 0 ,0
Exp/Cntr=0.3,0.1

Type RM Length L Ch R = 1 ,1922.4  ,258.2,253.1,244.9
XS GIS Cut Line= 3
     1571012.545      393522.968     1570993.605       393122.92
      1570950.62      393049.992
#Sta/Elev= 29
       0  771.59     9.8   771.3    39.1  770.67    68.4  769.88   136.8  768.34
   166.1  767.76   214.9  766.57   224.7  766.41   234.4  766.39     254   766.7
   263.7  766.73   273.5  766.52   283.3  766.09     293  765.45   302.8  764.57
   322.4   762.3   341.9  759.74   351.7  758.53   361.4  757.88   371.2  758.14
   373.6  758.51     381  759.65   390.7  762.02   400.5  764.62   409.9  767.53
   419.3  770.67   428.7  773.95   447.5  780.82   485.2  794.01
#Mann= 3 , 0 , 0
       0     .07       0   351.7    .045       0   373.6     .08       0
Bank Sta=351.7,373.6
XS Rating Curve= 0 ,0
Exp/Cntr=0.3,0.1

Type RM Length L Ch R = 1 ,1669.3  ,223.2,223.8,224.2
XS GIS Cut Line= 2
     1571339.064      393453.733      1571183.27      392986.434
#Sta/Elev= 24
       0  770.93    19.3  768.84      29  768.04    38.6  767.37      58  766.39
    86.9  765.27   144.9  763.44   212.5  761.01   289.8  758.42   318.7  757.35
     338  756.47   347.7   756.1   357.4  756.27   360.7  756.75     367  757.68
   386.3  763.01   405.7  767.56   415.3  770.08     425  773.02   434.6   776.3
   444.3  779.95     454  784.17   473.3  793.39   492.6  802.39
#Mann= 3 , 0 , 0
       0     .06       0     338    .045       0   360.7      .1       0
Bank Sta=338,360.7
XS Rating Curve= 0 ,0
Exp/Cntr=0.3,0.1

Type RM Length L Ch R = 1 ,1445.5  ,200,205.2,210
XS GIS Cut Line= 3
      1571495.78      393456.049     1571504.895      393259.434
     1571390.311      392889.642
#Sta/Elev= 26
       0  776.75    98.4  768.99   127.9  766.74     187  762.56   196.8  761.93
   225.9  760.46   264.6  758.28   293.6  757.06   322.6  756.04     342  755.47
   400.1  753.96   409.8  753.86   419.4  754.38   429.1  756.86   438.8  760.95
   448.5  764.74   477.5  774.39   496.9  781.12   516.2  788.09   525.9  791.72
   535.6  795.48   545.2  799.34   554.9  803.57   564.6  808.32   574.3  813.39
     584  818.57
#Mann= 3 , 0 , 0
       0     .06       0   400.1    .045       0   419.4      .1       0
Bank Sta=400.1,419.4
XS Rating Curve= 0 ,0
Exp/Cntr=0.3,0.1

Type RM Length L Ch R = 1 ,1240.4  ,170.7,165.9,160.9
XS GIS Cut Line= 3
     1571560.891      393460.105     1571657.246      393208.803
       1571628.6      392845.521
#Sta/Elev= 20
       0  774.82    28.8  772.87   115.4  767.32   144.2  765.56   163.4  764.29
     173  763.82   230.7  761.76   297.9  759.19   326.7  758.29   422.6  755.03
   458.6     754   460.9  753.93   470.5  753.94   480.1   755.1   489.7  758.05
   499.3  761.84   508.9  765.27   528.1  771.64   566.4  784.76   633.6  808.43
#Mann= 3 , 0 , 0
       0     .06       0   458.6    .045       0   480.1      .1       0
Bank Sta=458.6,480.1
XS Rating Curve= 0 ,0
Exp/Cntr=0.3,0.1

Type RM Length L Ch R = 1 ,1074.4  ,179.7,185,190
XS GIS Cut Line= 3
     1571973.586      393375.258     1571882.208      393233.724
      1571752.12      392805.928
#Sta/Elev= 30
       0  774.65     9.4  770.83    18.7   767.5    28.1  765.88    65.5  763.51
    74.9  763.16    84.2  763.04   140.4  762.85   187.9  762.47   197.6  762.18
   236.5  760.05     256  759.34   275.4  758.91   285.1  758.78   343.4   758.5
   353.2   758.4   362.9  758.15   372.6  757.67   411.5  755.28   430.9  753.95
   440.6   753.3   450.4  753.17   460.1  754.73   469.8  758.51   479.5  763.08
   489.2  767.25   547.6  790.15   596.2   809.4   605.9  813.62   615.6  818.15
#Mann= 3 , 0 , 0
       0     .06       0   430.9    .045       0   460.1      .1       0
Bank Sta=430.9,460.1
XS Rating Curve= 0 ,0
Exp/Cntr=0.3,0.1

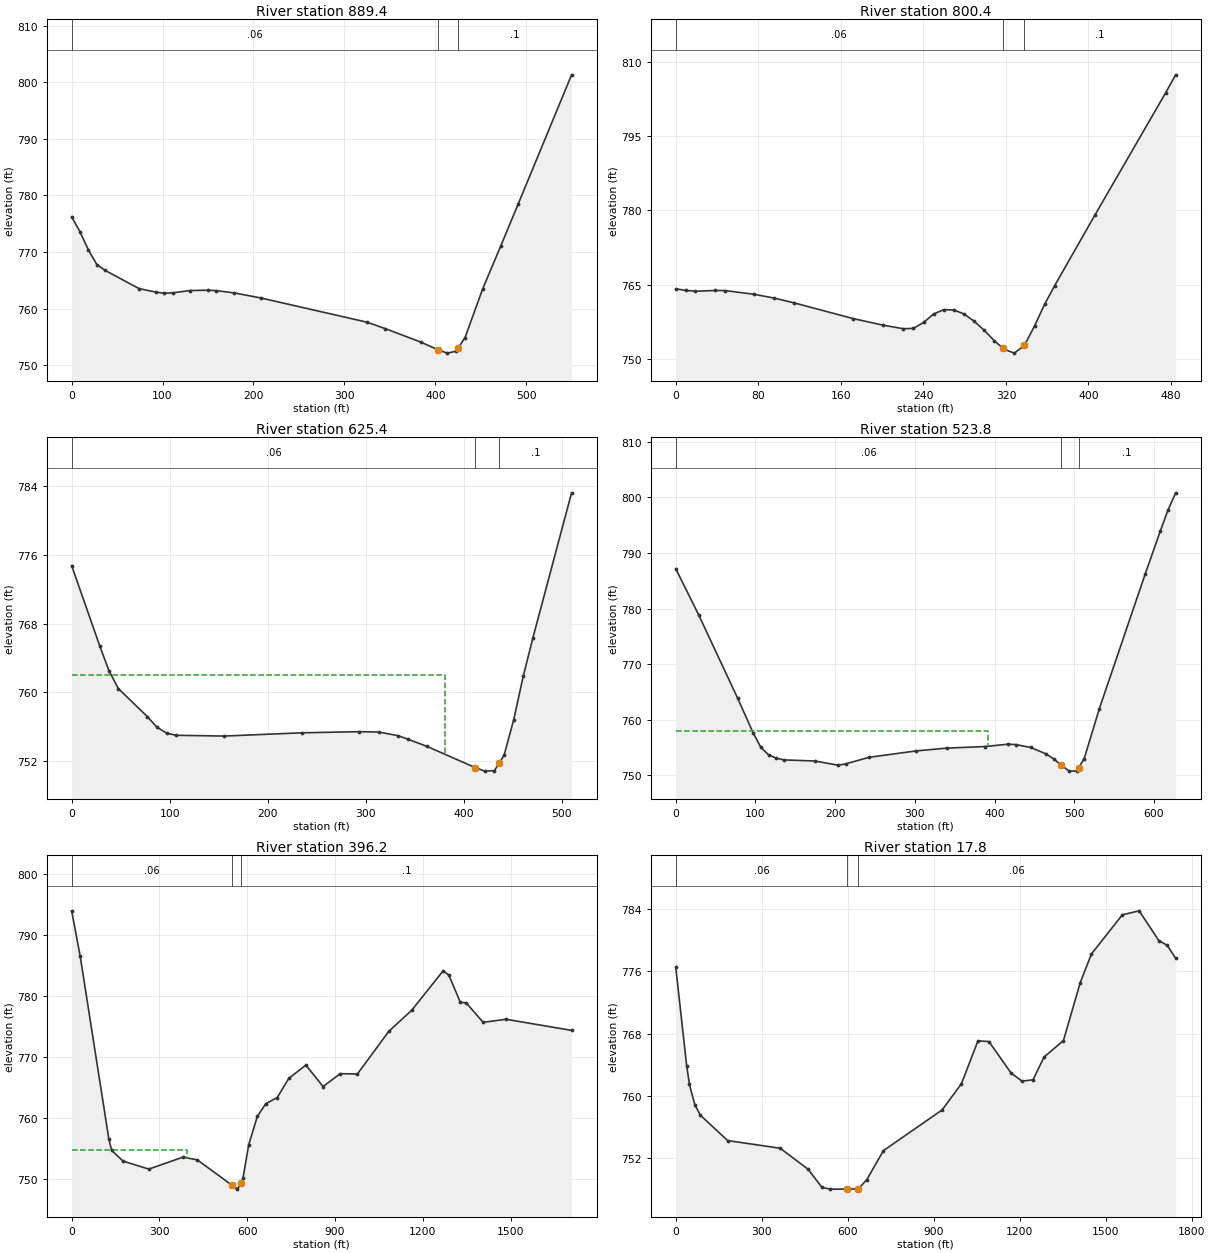
Type RM Length L Ch R = 1 ,889.4   ,91,89,87
XS GIS Cut Line= 3
     1572064.798       393319.48     1571999.303      393218.643
     1571970.429      392789.996
#Sta/Elev= 26
       0  776.23     9.2  773.58    18.5  770.35    27.8  767.77      37  766.75
      74  763.55    92.5  762.92   101.7  762.73     111  762.79     130   763.2
   149.5  763.26   159.3  763.18   178.8  762.78   208.1  761.89   325.3  757.59
   344.8  756.48   383.9   754.1   403.4   752.7   413.2  752.14   422.9  752.48
   424.9  752.97   432.7  754.89   452.2  763.53   471.8     771   491.3  778.54
   549.9  801.32
#Mann= 3 , 0 , 0
       0     .06       0   403.4    .045       0   424.9      .1       0
Bank Sta=403.4,424.9
XS Rating Curve= 0 ,0
Exp/Cntr=0.3,0.1

Type RM Length L Ch R = 1 ,800.4   ,184.4,175,165.4
XS GIS Cut Line= 3
     1572062.126      393230.163     1572091.274      393060.926
     1572042.292      392751.986
#Sta/Elev= 30
       0  764.15     9.5  763.84    19.1  763.66    38.2  763.82    47.7   763.8
    76.3  763.04    95.4  762.28   114.5  761.33   171.7  758.16     201  756.82
   220.6   756.1   230.4  756.17   240.2  757.37   249.9  759.07   259.7  759.95
   269.5  759.88   279.2   759.1     289  757.65   298.8  755.82   308.6   753.7
   316.7  752.25   318.4  751.94   328.1  751.18   337.9  752.72   347.7  756.64
   357.4  760.99   367.2  764.78   406.3  779.05   474.8  803.69   484.5  807.32
#Mann= 3 , 0 , 0
       0     .06       0   316.7    .045       0   337.9      .1       0
Bank Sta=316.7,337.9
XS Rating Curve= 0 ,0
Exp/Cntr=0.3,0.1

Type RM Length L Ch R = 1 ,625.4   ,100.8,101.6,102.4
XS GIS Cut Line= 3
     1572447.932      393204.545     1572434.611      393158.897
     1572181.767        392771.7
#Sta/Elev= 24
       0  774.76    28.5  765.44      38  762.52    47.6  760.42    77.1  757.16
    86.9  755.93    96.8  755.22   106.6  754.97   155.8  754.88   234.5  755.26
   293.5  755.39   313.2  755.35   332.9  754.93   342.7  754.53   362.4  753.68
   411.6  751.21   421.4  750.79   431.3  750.85   436.4  751.77   441.1  752.62
     451   756.8   460.8  761.91   470.6  766.36     510  783.25
#Mann= 3 , 0 , 0
       0     .06       0   411.6    .045       0   436.4      .1       0
#XS Ineff= 2 , 0
          380.74  761.96
Permanent Ineff=
       F       F
Bank Sta=411.6,436.4
XS Rating Curve= 0 ,0
Exp/Cntr=0.3,0.1

Type RM Length L Ch R = 1 ,523.8   ,123.7,127.6,131.4
XS GIS Cut Line= 3
     1572550.418      393224.456     1572379.651      392897.525
     1572246.279      392676.237
#Sta/Elev= 30
       0  787.17    29.1  778.76    77.6  763.87    97.1  757.62   106.8  754.99
   116.5  753.64   126.2  753.05   135.9  752.74   174.7  752.54   203.8  751.78
   213.5  752.04   242.7  753.21   300.9  754.35   339.7  754.86     388  755.15
   416.7  755.57   426.3  755.51   445.4  754.98   464.5  753.82   474.1  752.94
   483.7  751.81   493.2  750.76   502.8  750.72   505.5  751.35   512.4  752.96
   531.5  761.98   588.9  786.19   608.1  794.02   617.6  797.75   627.2  800.84
#Mann= 3 , 0 , 0
       0     .06       0   483.7    .045       0   505.5      .1       0
#XS Ineff= 2 , 0
          391.85  757.88
Permanent Ineff=
       F       F
Bank Sta=483.7,505.5
XS Rating Curve= 0 ,0
Exp/Cntr=0.3,0.1

Type RM Length L Ch R = 1 ,396.2   ,369.8,378.4,385.5
XS GIS Cut Line= 4
     1572626.372      393246.158     1572354.054      392556.226
     1572131.501      392013.427     1571922.632      391695.938
#Sta/Elev= 30
       0  793.95    29.3  786.48   126.9  756.64   136.6  754.72   175.7  752.96
   263.5  751.65   380.6  753.61   429.4  753.16   546.5  749.06   566.1  748.37
   579.8   749.3   585.6  750.19   605.1  755.64   634.4  760.27   663.6  762.37
   702.7  763.37   741.7  766.49   800.4  768.69   859.1  765.17   917.7  767.28
   976.4  767.22  1083.9  774.22  1162.2  777.67  1269.7  784.14  1289.3  783.39
  1328.4  778.96  1347.9   778.9  1406.3  775.68  1484.3  776.19  1708.4  774.37
#Mann= 3 , 0 , 0
       0     .06       0   546.5    .045       0   579.8      .1       0
#XS Ineff= 2 , 0
          395.39  754.77
Permanent Ineff=
       F       F
Bank Sta=546.5,579.8
XS Rating Curve= 0 ,0
Exp/Cntr=0.3,0.1

Type RM Length L Ch R = 1 ,17.8    ,17.3,17.8,18.3
XS GIS Cut Line= 5
     1572665.036      393203.967     1572790.347      392957.488
     1572767.746      392285.614     1572680.866      391911.323
     1572434.134       391582.44
#Sta/Elev= 30
       0  776.53    38.1  763.88    47.7  761.46    66.7  758.83    85.8  757.51
   181.2  754.24   364.2  753.26   461.6  750.56   510.3  748.22   539.6     748
     598     748     637  748.04   666.2   749.2   724.7  752.95   929.3  758.18
   996.8  761.55  1054.4  767.07  1092.8  766.97  1169.7  762.94  1208.1  761.88
  1246.6  762.06    1285  764.98  1352.6   767.1  1411.3  774.55  1450.5  778.24
  1558.2  783.27  1616.9  783.78  1685.4  779.96  1714.8  779.34  1744.2  777.68
#Mann= 3 , 0 , 0
       0     .06       0     598    .045       0     637     .06       0
Bank Sta=598,637
XS Rating Curve= 0 ,0
Exp/Cntr=0.3,0.1

Chan Stop Cuts=-1
Use User Specified Reach Order=0
Composite Channel Slope=5